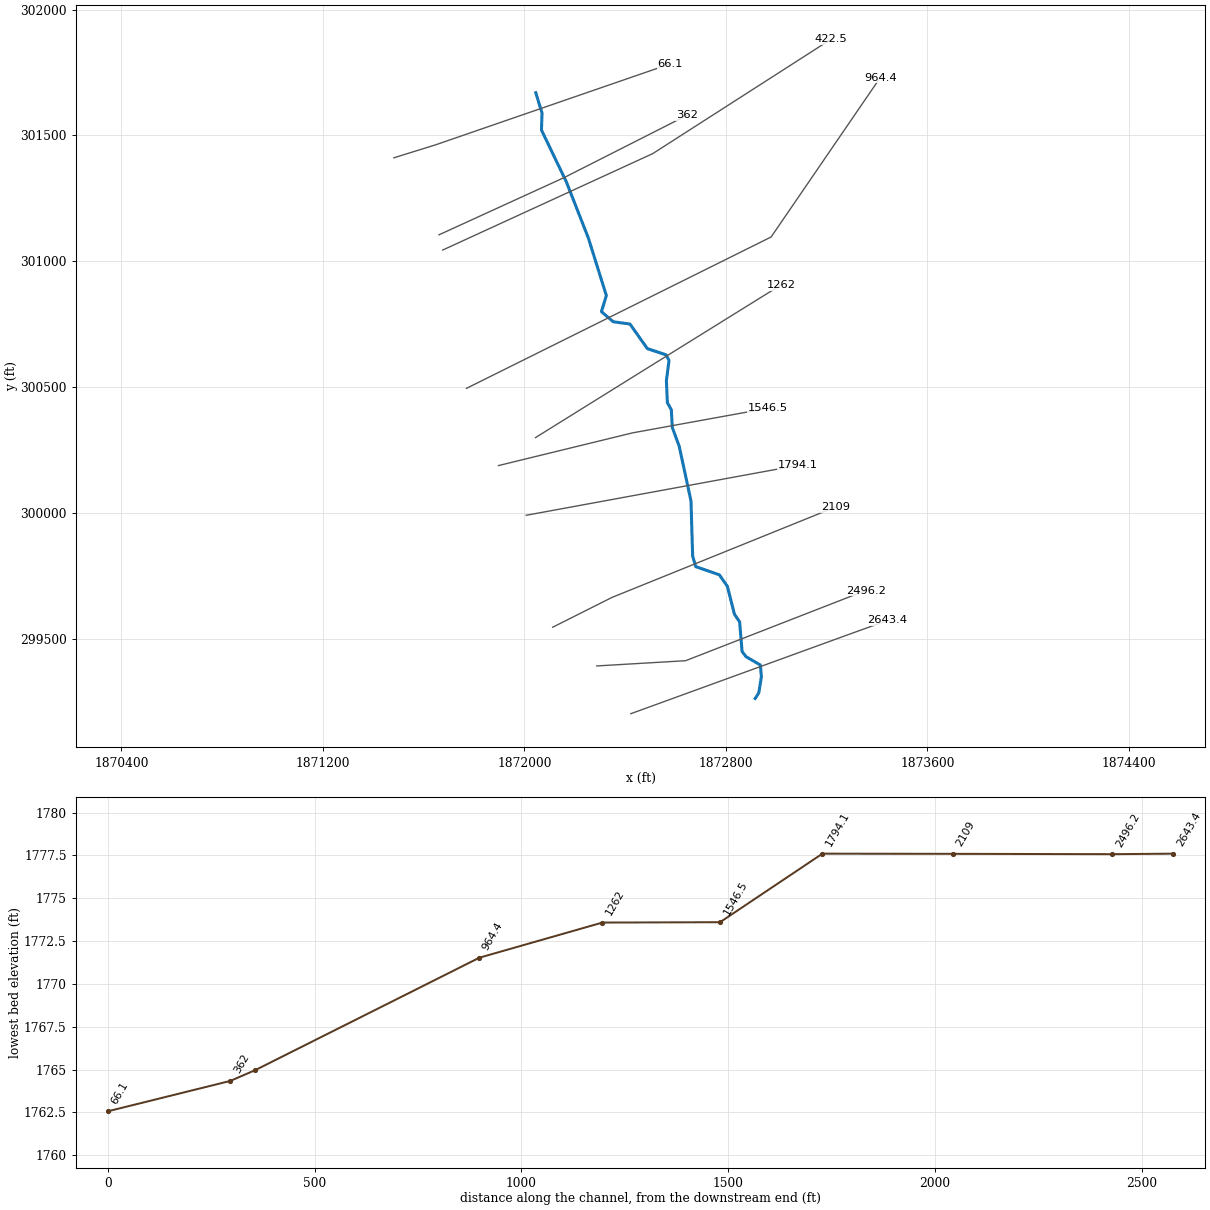
--- HrprBrnch.prj (project) ---

Proj Title=HrprBrnch
Current Plan=p01
Default Exp/Contr=0,0
English Units
Geom File=g01
Flow File=f01
Plan File=p01
BEGIN DESCRIPTION:
END DESCRIPTION:
DSS Export Rating Curves= 0
DSS Export Rating Curve Sorted= 0
DSS Export Volume Flow Curves= 0
DXF OffsetX= 0
DXF OffsetY= 0
DXF ScaleX= 0
DXF ScaleY= 0

--- HrprBrnch.p01 (plan) ---

Plan Title=Floodplain
Program Version=4.00
Geom File=g01
Flow File=f01
K Sum by GR=0
Std Step Tol=0.01
Critical Tol=0.01
Num of Std Step Trials=20
Max Error Tol=0.3
Flow Tol Ratio=0.001
Split Flow NTrial=30
Split Flow Tol=0.02
Split Flow Ratio=0.02
Log Output Level=0
Friction Slope Method=1
Unsteady Friction Slope Method=2
Unsteady Bridges Friction Slope Method=1
Global Log Level=0
CheckData=False
Run HTab=0
Run UNet=0
Run PostProcess=0
UNET Theta=0
UNET Theta Warmup=0
UNET ZTol=0
UNET ZSATol=0
UNET MxIter=0
UNET MaxInSteps=0
UNET DtIC=0
UNET DtMin=0
UNET MaxCRTS=0
UNET WFStab=0
UNET SFStab=0
UNET WFX=0
UNET SFX=0
UNET DSS MLevel=0
UNET DZMax Abort=0
UNET Convert EG Bridges=0
UNET Use Existing IB Tables=0
UNET Froude Limit=0
UNET Froude Power=0
Write IC File=0
Echo Input=False
Echo Output=False
Write Detailed=0

--- HrprBrnch.f01 (steady flow) ---

Flow Title=NFF Regression Equation
Program Version=4.00
Number of Profiles=1
Profile Names=P100yr
River Rch & RM=HrprBrnch,Main      ,2643.4
867.6026
River Rch & RM=HrprBrnch,Main      ,2109
894.6682
River Rch & RM=HrprBrnch,Main      ,422.5
967.8691
Boundary for River Rch & Prof#=HrprBrnch,Main      ,1
Up Type=0
Dn Type=3
Dn Slope=0.008758

--- HrprBrnch.g01 (geometry) ---

Geom Title=USGS 3m DEM
Program Version=4.10

River Reach=HrprBrnch       ,Main
Reach XY= 30
     1872916.107      299261.976     1872930.457      299284.744
     1872940.718      299348.722     1872936.685      299394.995
     1872879.836       299427.94     1872863.996      299448.655
     1872854.377      299566.218      1872833.54      299597.346
     1872805.838      299707.291     1872774.056      299753.213
     1872680.088      299786.078       1872667.8      299827.957
     1872661.294      300046.781     1872614.495       300264.35
     1872586.991      300339.376     1872583.244      300409.405
     1872567.524      300437.539     1872563.619      300524.808
     1872574.041      300605.564     1872562.319      300627.707
     1872488.076      300652.457     1872419.045      300750.148
     1872352.617      300759.268     1872305.728      300799.647
     1872325.267       300863.47     1872253.635      301092.715
     1872166.373      301315.449     1872067.739      301521.141
     1872069.905      301588.686      1872045.11      301669.595

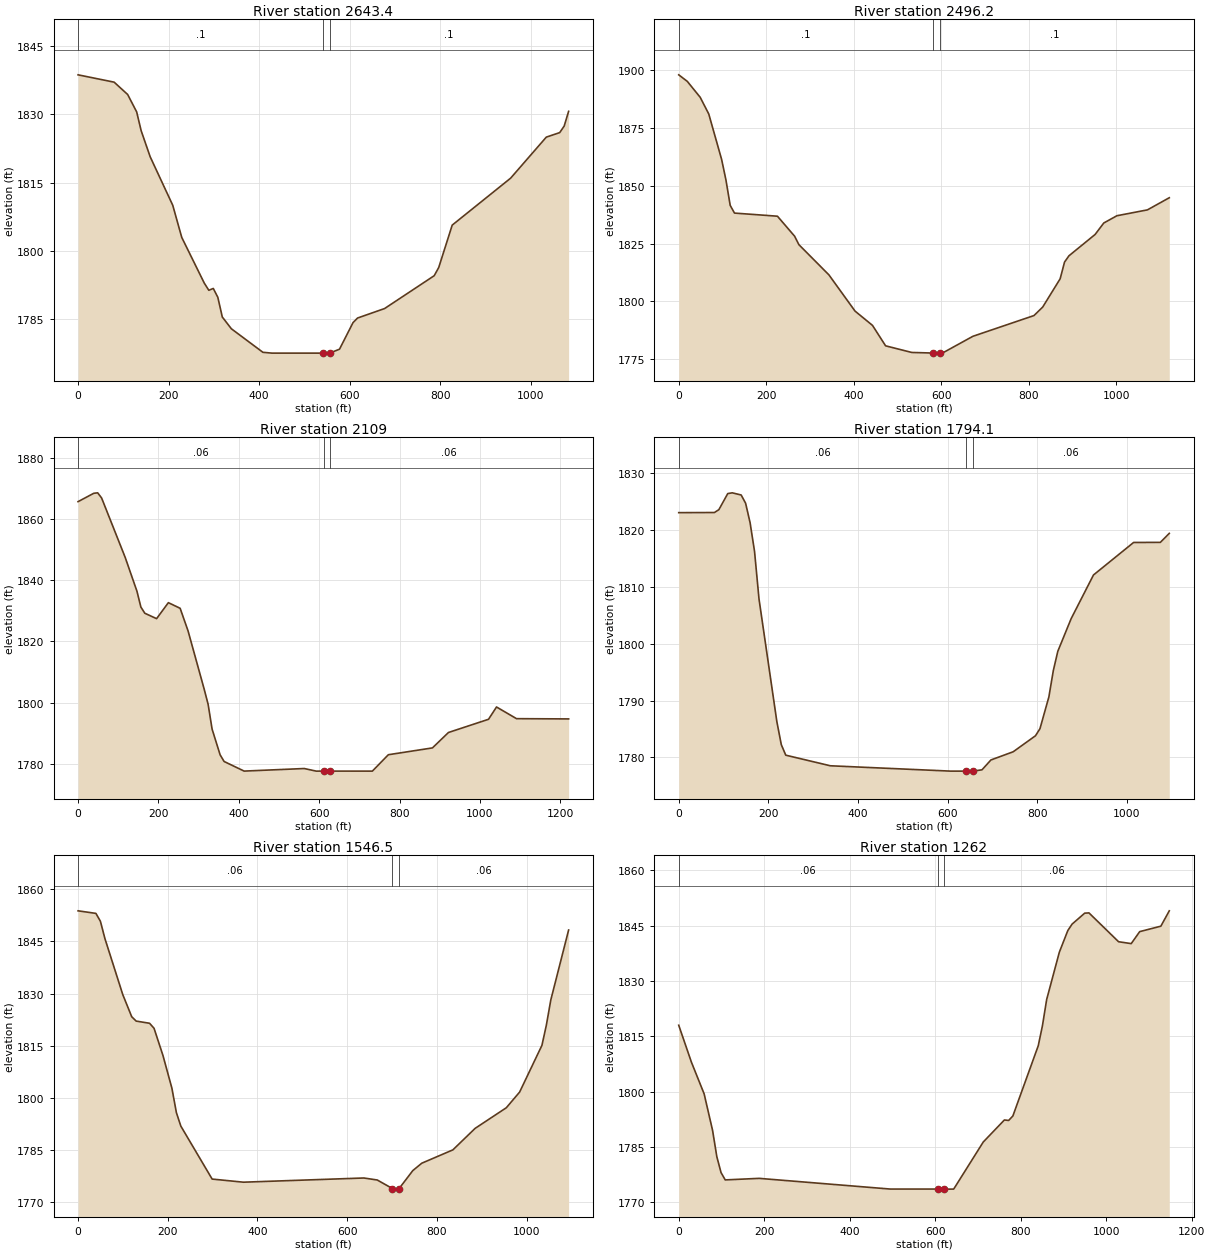
Type RM Length L Ch R = 1 ,2643.4  ,145.5,147.4,149
XS GIS Cut Line= 3
     1872422.494      299201.503     1873283.565      299515.063
     1873441.157      299571.926
#Sta/Elev= 30
       0 1838.71    79.7  1837.1   109.6 1834.39   129.5 1830.56   139.4 1826.44
   159.4  1820.7   209.2 1810.07   229.1 1803.01   278.9 1792.97   288.9  1791.4
   298.8  1791.8   308.8 1789.86   318.7 1785.53   338.7 1782.95   408.4 1777.78
   428.3  1777.6     541  1777.6     556  1777.6   577.7 1778.47   607.6 1784.31
   617.6 1785.31   677.3 1787.39   786.9  1794.6   796.9  1796.4   826.7 1805.71
   955.8 1816.02  1034.6 1825.03  1064.2 1826.02  1074.1 1827.46  1083.9 1830.69
#Mann= 3 , 0 , 0
       0      .1       0     541    .045       0     556      .1       0
Bank Sta=541,556
XS Rating Curve= 0 ,0
Exp/Cntr=0.3,0.1

Type RM Length L Ch R = 1 ,2496.2  ,387.6,386.5,385.1
XS GIS Cut Line= 3
     1872287.464      299391.323     1872639.792        299412.1
      1873355.05      299691.136
#Sta/Elev= 30
       0 1898.02    19.6 1895.18      49  1888.3    68.6 1881.08      98  1861.4
   107.8 1852.58   117.6 1841.51   127.4 1838.18   225.5 1836.83   264.7 1828.19
   274.5 1824.52   343.1 1811.44   402.8 1795.76   442.7 1789.57   472.6 1780.73
   532.4 1777.86   581.3  1777.6   596.3 1777.59   602.2 1777.57     672 1784.85
   811.6 1793.83   831.5  1797.5   871.4 1809.75   881.4 1816.97   891.4 1819.68
   951.2 1828.92   971.1 1833.89    1001 1837.03  1070.8 1839.57  1120.7 1844.82
#Mann= 3 , 0 , 0
       0      .1       0   581.3    .045       0   596.3      .1       0
Bank Sta=581.3,596.3
XS Rating Curve= 0 ,0
Exp/Cntr=0.3,0.1

Type RM Length L Ch R = 1 ,2109    ,319.3,314.8,310.2
XS GIS Cut Line= 3
     1872112.183      299545.119     1872347.759      299663.719
     1873234.825       300022.77
#Sta/Elev= 30
       0  1865.7    39.1 1868.43    48.8 1868.58    58.6 1866.89   117.2 1847.49
   146.5 1836.42   156.3 1831.23   166.1 1829.21   195.4 1827.44   224.7 1832.67
     254 1830.83   273.7 1823.44   313.6  1804.5   323.6 1799.45   333.5 1791.34
   353.5 1782.92   363.4 1780.74   413.3  1777.6   562.8 1778.44   592.7 1777.59
   611.3  1777.6   626.3  1777.6   732.3 1777.59   772.1 1782.95   881.8 1785.18
   921.7 1790.22  1021.4 1794.54  1041.3 1798.56  1091.1 1794.74  1220.7 1794.66
#Mann= 3 , 0 , 0
       0     .06       0   611.3    .045       0   626.3     .06       0
Bank Sta=611.3,626.3
XS Rating Curve= 0 ,0
Exp/Cntr=0.3,0.1

Type RM Length L Ch R = 1 ,1794.1  ,247.5,247.6,247.6
XS GIS Cut Line= 2
     1872007.235      299990.157     1873083.489      300188.028
#Sta/Elev= 30
       0    1823    79.6 1823.02    89.5 1823.52   109.4 1826.35   119.4 1826.48
   139.3  1826.1   149.2 1824.65   159.2 1821.23   169.1  1816.2   179.1 1807.82
   218.9 1786.29   228.8 1782.25   238.8  1780.4   338.2 1778.54   606.8  1777.6
   641.5  1777.6   656.5  1777.6   676.5 1777.83   696.4 1779.56   746.1    1781
   795.8 1783.81   805.8 1785.05   825.7 1790.63   835.6 1795.25   845.6 1798.64
   875.4 1804.38   925.2 1812.05  1014.7 1817.76  1074.4 1817.78  1094.3 1819.36
#Mann= 3 , 0 , 0
       0     .06       0   641.5    .045       0   656.5     .06       0
Bank Sta=641.5,656.5
XS Rating Curve= 0 ,0
Exp/Cntr=0.3,0.1

Type RM Length L Ch R = 1 ,1546.5  ,276.3,284.4,293.2
XS GIS Cut Line= 3
     1871896.945       300187.65     1872429.217      300317.673
     1872966.079      300415.269
#Sta/Elev= 30
       0 1853.84    39.8  1853.1    49.8 1850.83    59.8 1845.87    99.6 1829.71
   119.6 1823.31   129.5 1822.05   159.4 1821.42   169.4 1819.97   189.3 1812.11
   209.2  1802.7   219.2 1795.65   229.1 1791.77   298.9  1776.5   368.6  1775.6
   637.2 1776.81     667 1776.23   700.8 1773.77   706.7  1773.6   715.8 1773.78
   746.3 1778.95   766.2 1781.07   835.6 1784.92   885.2 1791.12   954.7 1797.06
   984.4 1801.59  1034.1 1815.05    1044 1820.89  1053.9 1828.15  1093.6  1848.3
#Mann= 3 , 0 , 0
       0     .06       0   700.8    .045       0   715.8     .06       0
Bank Sta=700.8,715.8
XS Rating Curve= 0 ,0
Exp/Cntr=0.3,0.1

Type RM Length L Ch R = 1 ,1262    ,299.3,297.5,294.8
XS GIS Cut Line= 3
     1872043.991      300298.807     1872564.661      300623.283
     1873018.161      300905.287
#Sta/Elev= 30
       0 1818.01    29.7 1807.99    59.4 1799.42    79.2 1789.49    89.1 1782.38
      99 1778.06   108.8 1776.08     188  1776.5   494.8  1773.6     606  1773.6
     621  1773.6   633.3 1773.58   643.2 1773.59   712.4 1786.36   761.8 1792.33
   771.7 1792.19   781.6 1793.41     841 1812.45   850.8 1817.89   860.7    1825
   890.4 1837.84   910.2 1843.69   920.1 1845.42   949.7  1848.4   959.6 1848.47
  1028.9 1840.65  1058.5 1840.14  1078.3 1843.39  1127.8 1844.87  1147.5 1849.03
#Mann= 3 , 0 , 0
       0     .06       0     606    .045       0     621     .06       0
Bank Sta=606,621
XS Rating Curve= 0 ,0
Exp/Cntr=0.3,0.1

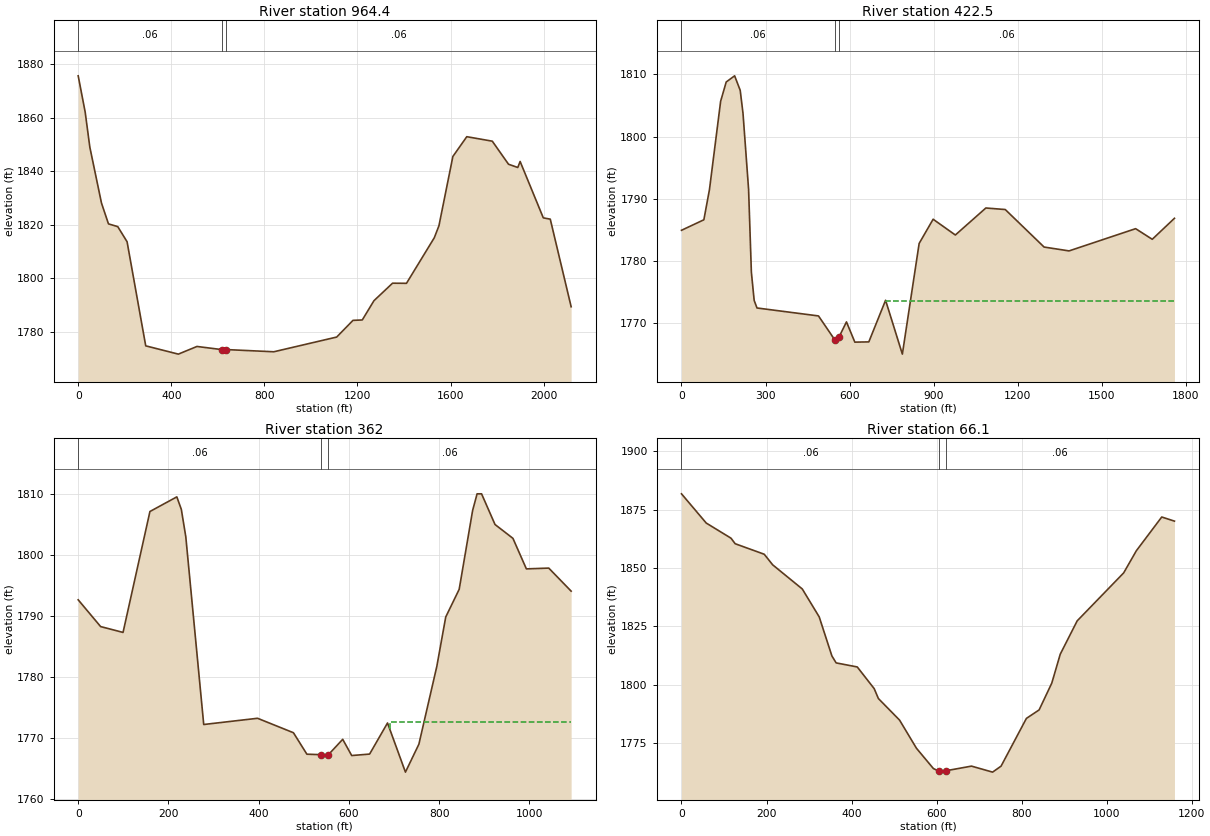
Type RM Length L Ch R = 1 ,964.4   ,542.7,541.9,541.2
XS GIS Cut Line= 3
     1871769.921      300494.599     1872979.357      301096.237
     1873412.455      301729.613
#Sta/Elev= 30
       0 1875.73      30 1862.17      50 1849.04   100.1 1828.09   130.1  1820.3
   170.1 1819.26   210.1  1813.6   290.2 1774.63   430.3 1771.53   510.3  1774.4
     618 1773.22     633 1773.25   840.5 1772.41  1110.7 1777.92  1180.7 1784.17
  1220.7 1784.32  1270.8 1791.53  1350.8 1798.09  1410.6 1798.04  1530.2 1815.12
  1550.1  1819.6  1609.9 1845.53  1669.7 1852.94  1779.3 1851.26  1849.1 1842.62
  1888.9 1841.41  1898.9 1843.66  1998.5 1822.55  2028.4 1822.07  2118.1 1789.28
#Mann= 3 , 0 , 0
       0     .06       0     618    .045       0     633     .06       0
Bank Sta=618,633
XS Rating Curve= 0 ,0
Exp/Cntr=0.3,0.1

Type RM Length L Ch R = 1 ,422.5   ,60.6,60.5,61.4
XS GIS Cut Line= 3
      1871675.69      301044.276     1872509.684      301427.697
     1873217.495      301882.331
#Sta/Elev= 30
       0 1784.91    79.8  1786.6    99.8 1791.46   139.7 1805.69   159.6 1808.79
   189.6 1809.78   209.5 1807.45   219.5 1803.74   239.4 1791.52   249.4 1778.14
   259.4 1773.61   269.4  1772.4   488.9 1771.12   547.8 1767.22   562.8 1767.78
   588.7 1770.16   618.6  1766.9   668.5 1766.94   728.3 1773.64   788.2 1764.97
   848.1 1782.79     898 1786.69   977.3 1784.15  1086.2  1788.5  1155.4 1788.25
    1294 1782.21  1383.1 1781.59  1620.6 1785.17    1680 1783.46  1759.2 1786.84
#Mann= 3 , 0 , 0
       0     .06       0   547.8    .045       0   562.8     .06       0
#XS Ineff= 2 , 0
                          729.77          1773.6
Permanent Ineff=
       F       F
Bank Sta=547.8,562.8
XS Rating Curve= 0 ,0
Exp/Cntr=0.3,0.1

Type RM Length L Ch R = 1 ,362     ,298.3,295.8,292.4
XS GIS Cut Line= 3
     1871660.874      301104.803     1872157.805      301332.327
     1872644.576       301579.44
#Sta/Elev= 30
       0  1792.6    49.7 1788.21    99.4 1787.25     159 1807.08   218.6 1809.48
   228.6 1807.42   238.5 1802.92   278.2 1772.15   397.5 1773.17     477  1770.8
   506.8 1767.28     539  1767.2     554 1767.16   586.2 1769.72   606.1 1767.06
   645.8  1767.3   685.5  1772.4   725.2 1764.34     755 1768.92   794.7 1781.67
   814.5 1789.78   844.3 1794.32   874.1 1807.26     884 1809.98   893.9 1809.98
   923.7 1804.95   963.4 1802.68   993.2 1797.67  1042.8  1797.8  1092.4 1794.02
#Mann= 3 , 0 , 0
       0     .06       0     539    .045       0     554     .06       0
#XS Ineff= 2 , 0
                          690.69         1772.48
Permanent Ineff=
       F       F
Bank Sta=539,554
XS Rating Curve= 0 ,0
Exp/Cntr=0.3,0.1

Type RM Length L Ch R = 1 ,66.1    ,66.8,66,65.2
XS GIS Cut Line= 3
     1871481.814      301410.908     1871648.613      301462.898
     1872579.303      301784.343
#Sta/Elev= 30
       0 1881.78    58.2 1869.26   116.5 1862.77   126.2 1860.41   194.6  1855.9
   214.5 1851.36   284.1 1841.02   323.9 1829.06   353.7 1812.35   363.7 1809.36
   413.4 1807.62   453.2 1798.33   463.1 1794.09   512.9 1784.85   552.6  1772.8
   592.4 1764.11   606.6 1762.84   621.6 1763.15     682 1765.14   731.7 1762.57
   751.6 1765.13   811.2 1785.58   841.1 1789.22   870.9 1800.71   890.8 1813.08
   930.6 1827.36    1040 1847.92  1069.8  1857.4  1129.5 1871.85  1159.4 1870.09
#Mann= 3 , 0 , 0
       0     .06       0   606.6    .045       0   621.6     .06       0
Bank Sta=606.6,621.6
XS Rating Curve= 0 ,0
Exp/Cntr=0.3,0.1

Chan Stop Cuts=-1
Use User Specified Reach Order=0
Composite Channel Slope=5